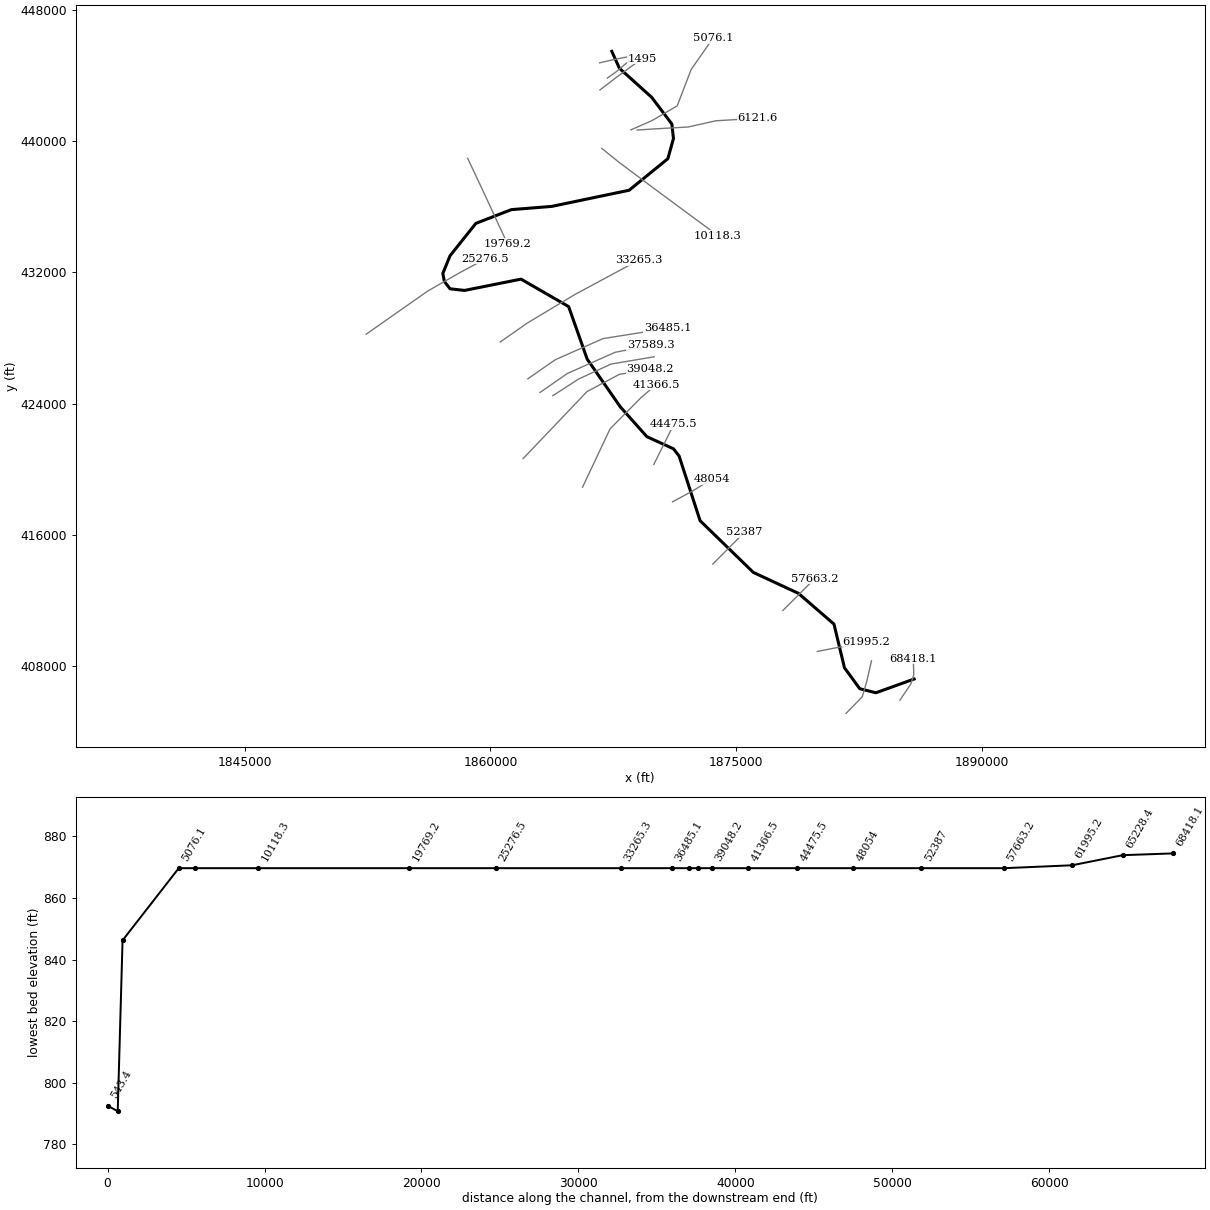
--- CheatRvr.prj (project) ---

Proj Title=CheatRvr
Current Plan=p01
Default Exp/Contr=0,0
English Units
Geom File=g01
Flow File=f01
Plan File=p01
BEGIN DESCRIPTION:
The 100-yr water surface elevation of the reservoir is 877 feet. At the first cross-section upstream of the dam (XS1495), a rating curve is set at this elevation. Downstream of the dam does not consider attenuation, and the flow will remain the same with normal depth condition (slope measured from ~34ft d/s of XS1187.1 with bottom of channel elevation of 795.09 to XS543.4 with bottom of channel elevation of 795.2)
END DESCRIPTION:
DSS Export Rating Curves= 0
DSS Export Rating Curve Sorted= 0
DSS Export Volume Flow Curves= 0
DXF OffsetX= 0
DXF OffsetY= 0
DXF ScaleX= 0
DXF ScaleY= 0

--- CheatRvr.p01 (plan) ---

Plan Title=Floodplain
Program Version=4.00
Geom File=g01
Flow File=f01
K Sum by GR=0
Std Step Tol=0.01
Critical Tol=0.01
Num of Std Step Trials=20
Max Error Tol=0.3
Flow Tol Ratio=0.001
Split Flow NTrial=30
Split Flow Tol=0.02
Split Flow Ratio=0.02
Log Output Level=0
Friction Slope Method=1
Unsteady Friction Slope Method=2
Unsteady Bridges Friction Slope Method=1
Global Log Level=0
CheckData=False
Run HTab=0
Run UNet=0
Run PostProcess=0
UNET Theta=0
UNET Theta Warmup=0
UNET ZTol=0
UNET ZSATol=0
UNET MxIter=0
UNET MaxInSteps=0
UNET DtIC=0
UNET DtMin=0
UNET MaxCRTS=0
UNET WFStab=0
UNET SFStab=0
UNET WFX=0
UNET SFX=0
UNET DSS MLevel=0
UNET DZMax Abort=0
UNET Convert EG Bridges=0
UNET Use Existing IB Tables=0
UNET Froude Limit=0
UNET Froude Power=0
Write IC File=0
Echo Input=False
Echo Output=False
Write Detailed=0

--- CheatRvr.f01 (steady flow) ---

Flow Title=NFF Regression Equation
Program Version=4.10
Number of Profiles= 1
Profile Names=P100yr
River Rch & RM=CheatRvr,Main            ,68418.1
   95062
River Rch & RM=CheatRvr,Main            ,41366.5
   95809
River Rch & RM=CheatRvr,Main            ,36485.1
   96093
River Rch & RM=CheatRvr,Main            ,543.4
   97986
Boundary for River Rch & Prof#=CheatRvr,Main            , 1
Up Type= 0
Dn Type= 3
Dn Slope=0.00425
DSS Import GetInterval= 0
DSS Import GetPeak= 0
DSS Import FillOption= 0

--- CheatRvr.g01 (geometry) ---

Geom Title=USGS 10m DEM
Program Version=4.10

River Reach=CheatRvr        ,Main
Reach XY= 30
     1885857.839      407228.097     1883523.024      406389.309
     1882538.784      406635.369     1881603.756      407914.881
        1880964.      410572.329     1878798.671      412442.385
     1876042.799      413721.897     1872794.807      416871.465
     1871515.295      420808.425     1871170.811      421251.333
     1869546.815      421989.513     1867922.819      423810.357
     1865905.127      426713.866     1864773.251      429912.646
     1861869.743      431585.854     1858424.903      430896.886
     1857539.087       430995.31     1857194.603      431438.218
     1857096.179      431930.338     1857539.087      433013.002
     1859113.871      434981.482     1861279.199      435818.086
     1863739.799      436014.934     1868464.151      436999.174
     1870826.327      438918.442     1871170.811      440148.742
     1871072.387      441034.558     1869842.087      442658.554
     1867873.607      444430.186     1867406.711      445460.153

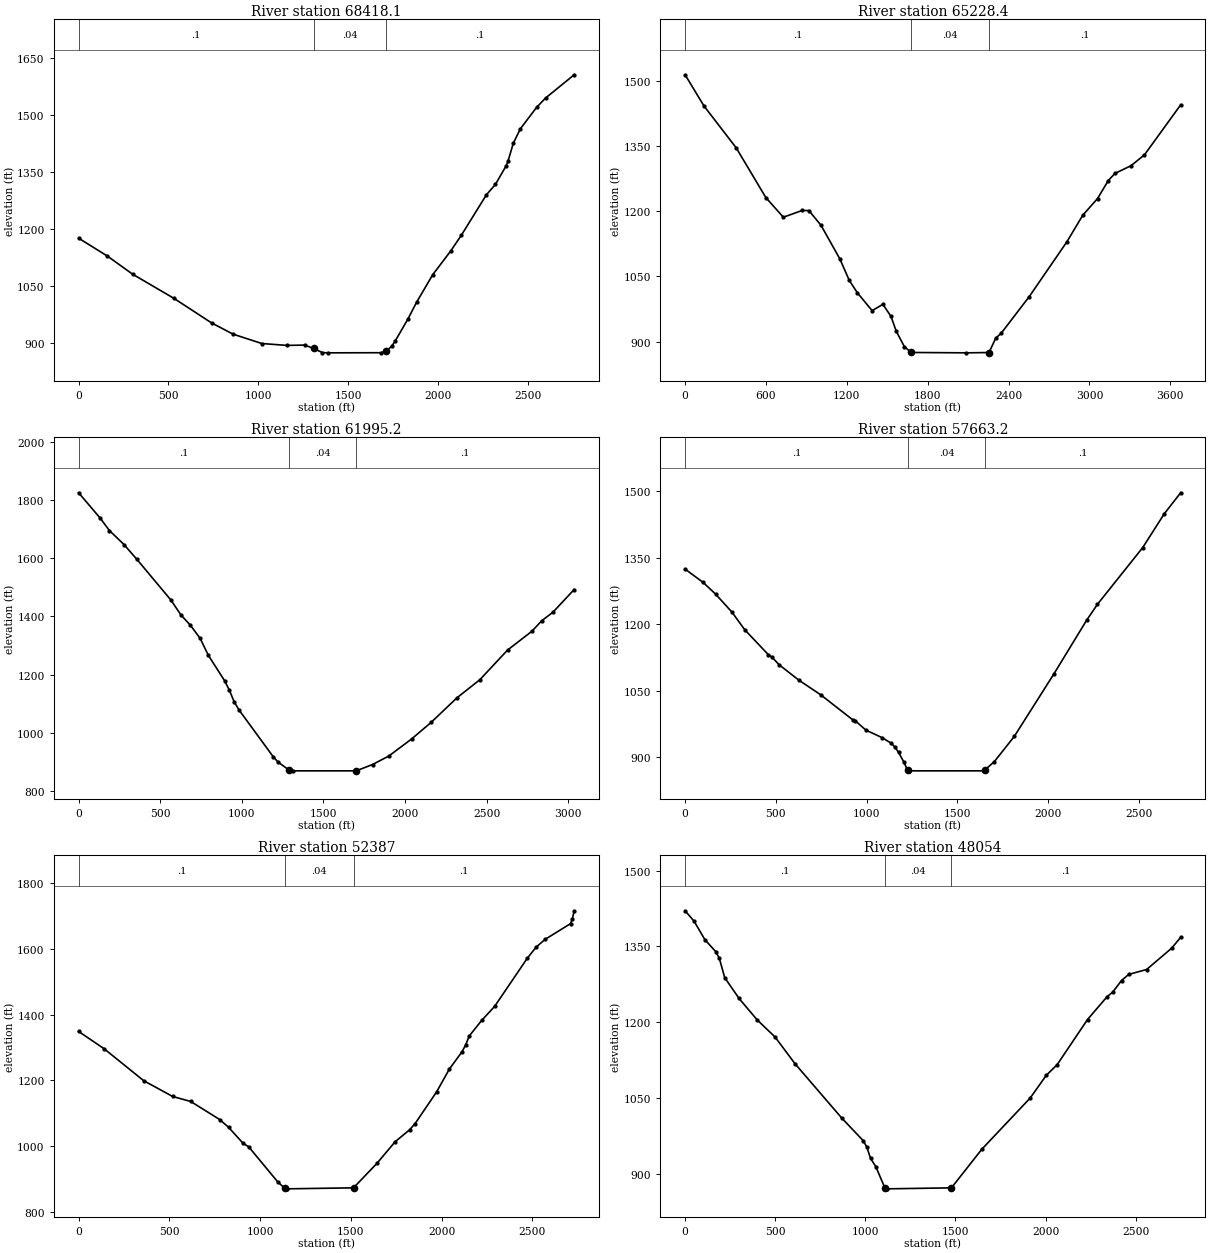
Type RM Length L Ch R = 1 ,68418.1 ,3188.8,3189.7,3191
XS GIS Cut Line= 4
     1884989.422      405940.761     1885650.157      406917.902
     1885834.532      407480.923     1885803.282      408467.034
#Sta/Elev= 30
       0 1176.37   159.9 1129.31   299.9 1081.77   529.8 1018.14   739.7  953.43
   859.7  923.71  1019.6  899.06  1159.6  894.06  1258.6  894.92  1307.9  885.95
  1357.3  875.17  1386.9   874.5  1683.1  874.82  1712.8  878.89  1742.4  891.74
  1762.1   905.6  1831.8  962.38  1881.6  1007.9  1971.3  1080.3    2071 1142.43
  2130.8 1184.36  2270.3 1290.76  2320.1 1317.82  2379.9 1366.98  2389.9  1378.4
  2419.8 1426.44  2459.6 1464.72  2549.3  1520.7  2599.2 1545.31  2758.6  1606.6
#Mann= 3 , 0 , 0
       0      .1       0  1307.9     .04       0  1712.8      .1       0
Bank Sta=1307.9,1712.8
XS Rating Curve= 0 ,0
Exp/Cntr=0.3,0.1

Type RM Length L Ch R = 1 ,65228.4 ,3258.7,3233.2,3207.8
XS GIS Cut Line= 4
     1881702.964      405134.337     1882692.547      406149.962
     1882965.985      407087.462     1883252.443      408337.462
#Sta/Elev= 30
       0 1514.01   139.8  1442.4   379.4 1345.71   599.1 1231.37   728.9 1186.13
   868.6 1201.66   918.6  1201.4  1008.4 1167.53  1148.2  1090.2  1218.1 1040.76
    1278 1012.25  1387.8  971.03  1467.6  985.67  1527.4  957.93  1567.3  923.23
    1627   888.2  1677.1874.7787  2085.4  873.93  2255.1874.6329  2304.7  907.76
  2344.5  918.71  2553.4 1003.35  2831.8 1129.03    2951 1190.88  3060.4 1229.12
  3139.9 1270.57  3189.6 1286.95  3308.9 1304.78  3408.3 1329.67  3676.8 1444.67
#Mann= 3 , 0 , 0
       0      .1       0  1677.1     .04       0  2255.1      .1       0
Bank Sta=1677.1,2255.1
XS Rating Curve= 0 ,0
Exp/Cntr=0.3,0.1

Type RM Length L Ch R = 1 ,61995.2 ,4318,4331.9,4345.9
XS GIS Cut Line= 4
     1879945.152      408906.038     1881056.263      409123.052
     1881880.915      409270.622     1882922.582      409496.316
#Sta/Elev= 30
       0  1824.3   129.1 1739.39   188.7 1694.82   278.1 1646.64   357.5 1595.63
     566 1455.93   625.6  1406.1   685.2 1369.63   744.8 1324.66   794.5 1266.86
   893.8 1180.08   923.6 1146.95   953.4 1106.67   983.1 1079.04  1191.9  919.11
  1221.9   900.6  1291.7  872.31  1311.6  870.64  1700.6  870.64  1800.3  892.28
    1900  921.35  2039.6  979.84  2159.1 1036.66  2318.5 1121.52    2458 1183.22
  2627.3 1284.68  2776.7 1349.32  2836.5 1385.09  2906.2 1414.99  3035.7 1492.52
#Mann= 3 , 0 , 0
       0      .1       0  1291.7     .04       0  1700.6      .1       0
Bank Sta=1291.7,1700.6
XS Rating Curve= 0 ,0
Exp/Cntr=0.3,0.1

Type RM Length L Ch R = 1 ,57663.2 ,5276.2,5276.2,5276.2
XS GIS Cut Line= 3
     1877847.802      411400.686     1878813.003      412365.887
     1879778.204      413331.088
#Sta/Elev= 30
       0 1324.83    99.6 1294.66   169.4 1267.86     259 1227.26   328.8 1187.87
   458.3 1131.89   478.2 1126.34   518.1 1108.96   627.7 1073.96   747.3  1041.2
   926.6  983.83   936.6  982.89   996.4  961.47    1086  944.48  1135.8  931.88
  1155.8  923.45  1175.7  911.53  1205.6  889.25  1225.5  870.83  1235.5   869.7
    1644  869.71  1653.9  872.57  1703.8  890.55  1813.4  947.26  2032.6 1088.91
  2211.9  1209.3  2271.7  1245.4  2520.8 1373.22  2640.3 1449.88    2730 1496.98
#Mann= 3 , 0 , 0
       0      .1       0  1225.5     .04       0  1653.9      .1       0
Bank Sta=1225.5,1653.9
XS Rating Curve= 0 ,0
Exp/Cntr=0.3,0.1

Type RM Length L Ch R = 1 ,52387   ,4339.2,4333,4327.7
XS GIS Cut Line= 3
     1873570.591      414230.384     1874535.791      415195.585
     1875500.992      416160.786
#Sta/Elev= 30
       0 1349.18   139.5 1296.87   358.7 1199.11   518.1 1151.09   617.7 1135.82
   777.2 1080.78     827 1056.61   906.7 1008.01   936.6  997.92    1096  891.52
  1135.8  871.16  1145.8   869.7  1514.4  872.75    1644   947.7  1743.6 1013.18
  1823.3 1049.58  1853.2 1068.12  1972.8 1165.67  2042.5 1234.72  2112.3 1287.45
  2132.2 1308.16  2152.1 1335.54  2221.9 1383.73  2291.6  1425.4    2471 1571.72
  2520.8 1606.37  2570.6 1630.03  2710.1 1677.72    2720 1692.27    2730 1716.86
#Mann= 3 , 0 , 0
       0      .1       0  1135.8     .04       0  1514.4      .1       0
Bank Sta=1135.8,1514.4
XS Rating Curve= 0 ,0
Exp/Cntr=0.3,0.1

Type RM Length L Ch R = 1 ,48054   ,3563.6,3578.5,3592.3
XS GIS Cut Line= 3
     1871115.494      418020.607     1872327.964      418676.004
     1873496.136      419393.649
#Sta/Elev= 30
       0 1420.39    49.9 1399.73   109.9 1363.12   169.8 1339.53   189.8 1326.38
   219.7 1288.05   299.6 1246.67   399.5 1204.45   499.4 1170.31   609.2 1117.75
   868.9 1009.96   988.8  964.87  1008.7  951.94  1028.7  930.28  1058.7   913.3
  1108.6  871.17  1118.6   869.7  1477.6  871.66  1646.5  948.22  1914.8 1049.63
  2004.2 1094.67  2063.8  1115.4  2232.7 1205.04  2341.9 1250.55  2371.8 1259.01
  2421.4 1282.24  2461.2 1294.33  2560.5 1304.07  2699.6 1346.34  2749.3  1367.8
#Mann= 3 , 0 , 0
       0      .1       0  1108.6     .04       0  1477.6      .1       0
Bank Sta=1108.6,1477.6
XS Rating Curve= 0 ,0
Exp/Cntr=0.3,0.1

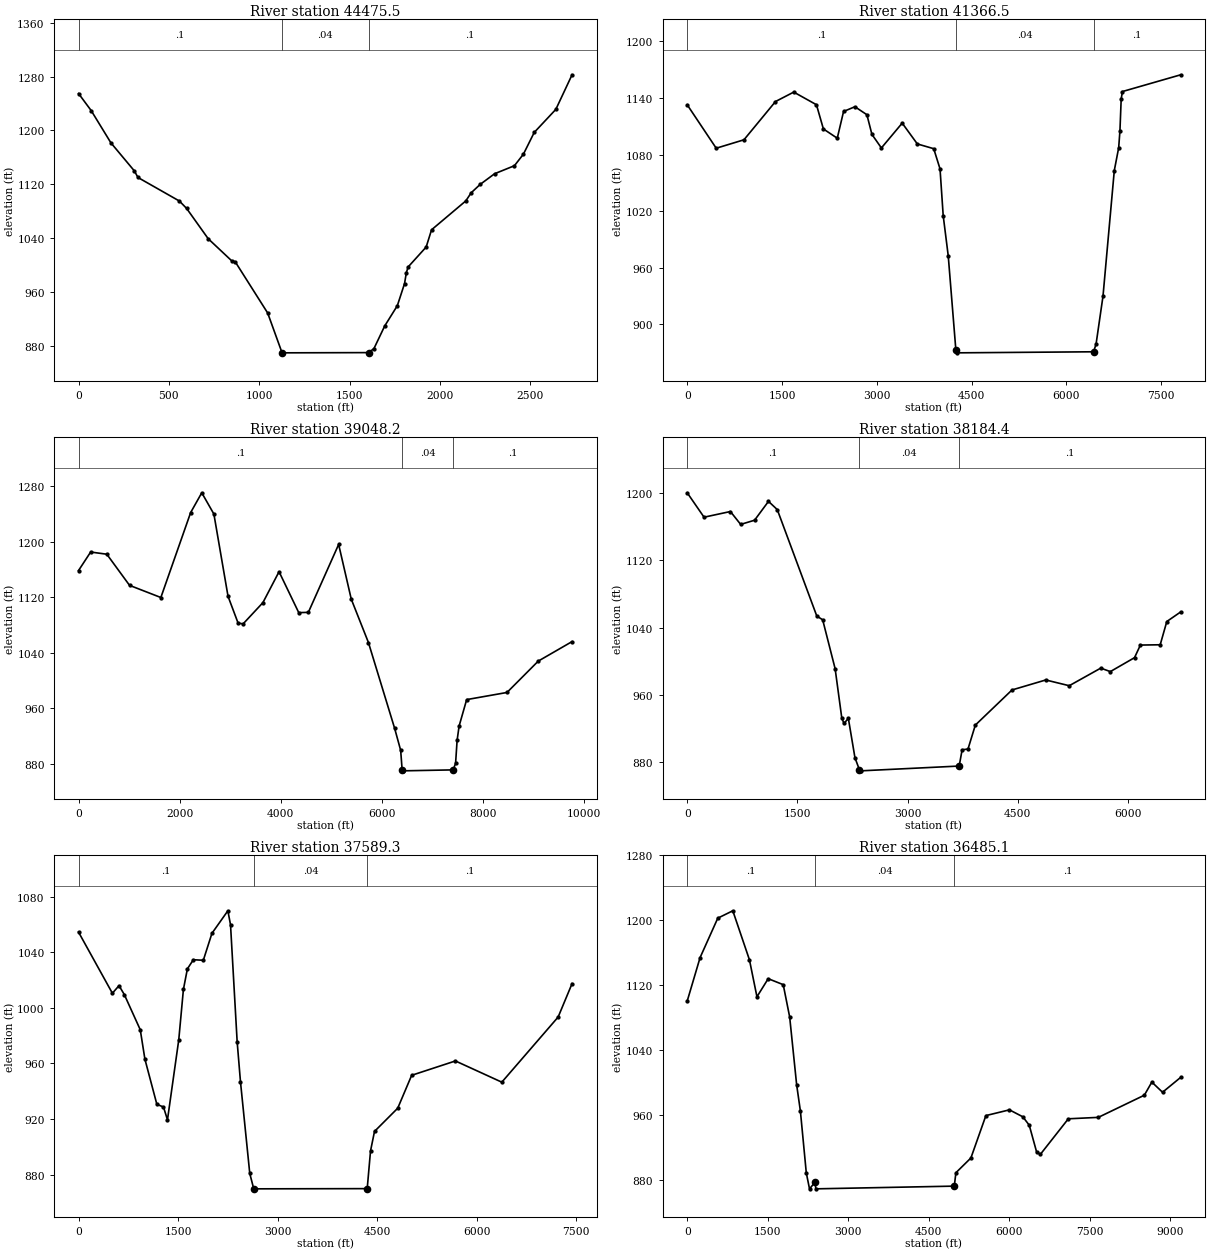
Type RM Length L Ch R = 1 ,44475.5 ,3116.3,3109,3101.8
XS GIS Cut Line= 3
     1869972.209      420299.912     1870582.656      421520.805
     1871193.102      422741.698
#Sta/Elev= 30
       0 1254.74    69.7 1229.51   179.3 1181.43   308.9  1139.8   328.8 1130.05
     558 1095.08   597.8 1084.16   717.4  1039.1   846.9 1006.44   866.8 1004.89
  1046.2  928.89  1125.9   869.7  1604.1  870.04    1634  875.97  1693.8  909.65
  1763.5  939.71  1803.4  972.57  1813.4  988.77  1823.3  997.24    1923 1026.81
  1952.8 1052.39  2142.2 1095.28    2172 1107.34  2221.9 1119.84  2301.6 1135.63
  2411.2 1147.54    2461 1164.71  2520.8 1196.99  2640.3 1231.21    2730 1282.56
#Mann= 3 , 0 , 0
       0      .1       0  1125.9     .04       0  1604.1      .1       0
Bank Sta=1125.9,1604.1
XS Rating Curve= 0 ,0
Exp/Cntr=0.3,0.1

Type RM Length L Ch R = 1 ,41366.5 ,2326.4,2318.3,2310
XS GIS Cut Line= 4
     1865622.235      418910.379     1867301.922      422465.066
     1869189.943      424366.108     1870101.402      425147.358
#Sta/Elev= 30
       0 1132.72     459 1086.67   898.1 1095.61    1397 1136.17  1686.4 1146.19
  2045.6 1132.78  2155.4  1107.1  2374.9 1097.29  2474.7 1125.65  2654.3 1130.66
  2843.9  1122.2  2923.7  1101.3  3073.4 1086.96  3402.7 1113.29  3642.2 1091.21
  3901.6 1086.18  4001.5 1064.74  4051.5 1015.27  4131.5  972.47  4251.5  873.15
  4271.5   869.7  6430.9  870.82  6470.9  878.83  6580.8  929.76  6759.7    1063
  6829.1 1087.21    6849 1105.13  6868.8 1138.93  6888.6 1146.78  7811.3 1164.55
#Mann= 3 , 0 , 0
       0      .1       0  4251.5     .04       0  6430.9      .1       0
Bank Sta=4251.5,6430.9
XS Rating Curve= 0 ,0
Exp/Cntr=0.3,0.1

Type RM Length L Ch R = 1 ,39048.2 ,865.3,863.8,862.4
XS GIS Cut Line= 4
     1861998.971      420656.906       1865892.2      424732.427
     1867871.367      425787.115     1869733.346      426086.594
#Sta/Elev= 30
       0 1158.33   239.8    1185   559.6 1181.86  1009.3 1136.99  1628.9 1119.47
  2218.5 1241.89  2438.4 1270.39  2678.2 1239.73    2958 1121.22  3157.9 1082.42
  3257.8 1081.59  3647.6 1112.05  3967.4 1156.66  4357.1  1097.7    4547 1098.05
  5146.6 1195.97  5396.4 1117.07  5735.9  1054.6  6254.2  930.98  6373.8  899.23
  6403.7  870.24  6413.7   869.7  7410.4  871.08  7460.2  880.31  7490.2  913.56
    7530  934.24  7679.5  972.35  8477.6  982.64  9096.2 1027.84  9764.8 1055.94
#Mann= 3 , 0 , 0
       0      .1       0  6403.7     .04       0  7410.4      .1       0
Bank Sta=6403.7,7410.4
XS Rating Curve= 0 ,0
Exp/Cntr=0.3,0.1

Type RM Length L Ch R = 1 ,38184.4 ,595.5,595.1,594.7
XS GIS Cut Line= 4
     1863808.867      424485.031     1865384.388      425500.656
     1867363.554      426412.115     1869993.763      426854.823
#Sta/Elev= 30
       0 1200.41   229.3 1171.36   588.3 1178.12   727.9 1162.79   917.3 1167.78
  1106.8 1190.19  1226.4  1180.4  1764.8 1053.78  1844.6 1049.37  2014.4  991.13
  2104.4  932.86  2134.4  926.03  2194.4  932.09  2284.3  885.26  2344.3  871.17
  2364.3   869.7  3703.6   875.4  3743.6  894.76  3823.6  895.63  3923.5  924.11
  4423.1   965.9  4882.6  977.77  5202.3  970.94  5631.8  991.88  5761.7  987.72
  6091.3  1004.3  6171.2 1019.29    6441 1019.64  6530.9 1047.29  6720.7 1058.74
#Mann= 3 , 0 , 0
       0      .1       0  2344.3     .04       0  3703.6      .1       0
Bank Sta=2344.3,3703.6
XS Rating Curve= 0 ,0
Exp/Cntr=0.3,0.1

Type RM Length L Ch R = 1 ,37589.3 ,1103.4,1104.2,1104.9
XS GIS Cut Line= 4
     1863027.617      424680.344     1864694.283      425839.198
      1867610.95      427128.261     1869785.429      427557.948
#Sta/Elev= 30
       0 1054.48     510 1010.48     610 1015.94     690 1009.49     930  984.21
    1000  963.03    1180  930.55    1280  928.58    1340  919.38    1510  976.96
    1580 1013.18    1640 1028.04    1730  1034.6    1880 1034.21    2010 1053.61
  2249.9 1069.83  2289.9 1059.77  2389.8  975.53  2439.8  946.76  2579.8  880.75
  2639.7   869.7  4349.1  869.85  4399.1  896.99  4459.1  911.03  4808.9  927.74
  5018.9  951.42  5678.1  961.74    6377  946.47  7225.6  993.35  7435.3  1017.4
#Mann= 3 , 0 , 0
       0      .1       0  2639.7     .04       0  4349.1      .1       0
Bank Sta=2639.7,4349.1
XS Rating Curve= 0 ,0
Exp/Cntr=0.3,0.1

Type RM Length L Ch R = 1 ,36485.1 ,3216,3219.8,3223.4
XS GIS Cut Line= 4
     1862285.429      425513.677     1863952.096      426672.531
     1866868.763      427961.594     1870801.054      428586.594
#Sta/Elev= 30
       0 1100.65     240 1154.12     570 1202.62     850 1211.69    1160  1151.4
    1300 1105.93    1510 1128.17    1790 1120.82    1910 1081.11    2040  997.73
  2109.9  965.41  2219.9  889.33  2279.9  869.71  2379.8  877.51  2399.8   869.7
  4978.9  873.04  5008.9   889.5  5288.6  907.66    5568  959.79  6007.1  966.86
  6256.6   958.3  6376.4  947.94  6516.1  914.44  6585.9   912.3  7104.8  955.84
  7663.7   957.6  8521.9  984.86  8661.6 1000.98  8861.2  988.49  9200.4 1006.85
#Mann= 3 , 0 , 0
       0      .1       0  2379.8     .04       0  4978.9      .1       0
Bank Sta=2379.8,4978.9
XS Rating Curve= 0 ,0
Exp/Cntr=0.3,0.1

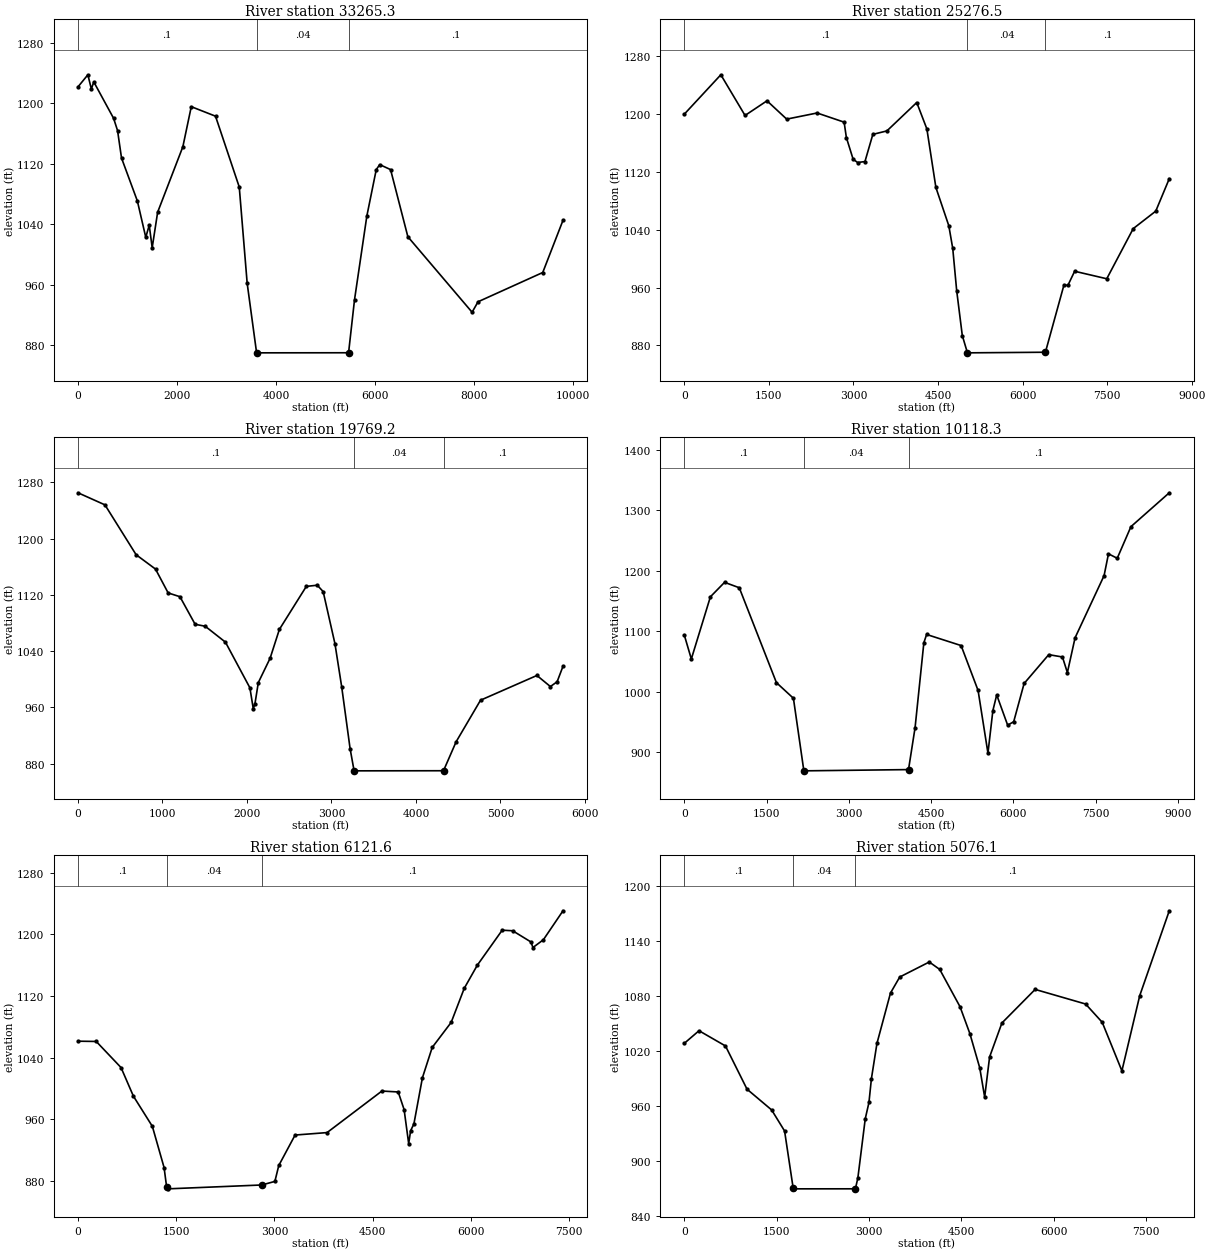
Type RM Length L Ch R = 1 ,33265.3 ,7988.7,7988.8,7989.4
XS GIS Cut Line= 4
     1860603.138      427761.073     1862269.804      428919.927
     1865160.429      430651.698     1869040.638      432735.031
#Sta/Elev= 30
       0  1221.6     200  1237.6     270 1218.85     320  1228.1     720 1179.98
     800 1163.74     880 1127.47    1200  1070.7    1370  1022.6    1440 1038.48
    1500 1008.82    1610 1055.72    2120 1142.41  2289.9  1195.4  2779.9 1182.82
  3259.8  1089.1  3419.8  961.76  3609.8  869.98  3619.8   869.7  5469.5  869.81
  5589.4  939.83    5839 1050.82  6028.8 1112.09  6098.7 1118.75  6318.4 1112.15
  6667.9  1023.3  7966.2  923.41    8086  937.26  9394.3  975.99  9803.8  1045.1
#Mann= 3 , 0 , 0
       0      .1       0  3609.8     .04       0  5469.5      .1       0
Bank Sta=3609.8,5469.5
XS Rating Curve= 0 ,0
Exp/Cntr=0.3,0.1

Type RM Length L Ch R = 1 ,25276.5 ,5545.6,5507.2,5468.4
XS GIS Cut Line= 4
     1852426.257      428234.996     1856165.638      430852.219
     1858118.763      431972.011     1859694.283      432818.365
#Sta/Elev= 30
       0  1199.5     649 1254.03  1078.4  1197.8  1467.8 1218.05  1817.3 1192.73
  2356.4 1201.22  2835.7 1188.54  2875.7 1167.24  2995.5 1137.29  3075.4 1132.76
  3205.2  1134.1    3345 1171.66  3594.6 1176.44  4123.8  1215.7  4303.5 1179.16
  4463.3 1098.28  4692.6 1045.35  4762.4 1013.96  4832.1  955.67  4931.7  893.66
  5021.4  870.07  5031.3   869.7    6406  870.53  6734.8  963.46  6804.5  962.94
  6924.4  982.46  7493.9  972.09  7963.5 1041.39  8363.1 1065.56  8602.9  1110.4
#Mann= 3 , 0 , 0
       0      .1       0  5021.4     .04       0    6406      .1       0
Bank Sta=5021.4,6406
XS Rating Curve= 0 ,0
Exp/Cntr=0.3,0.1

Type RM Length L Ch R = 1 ,19769.2 ,9639.7,9651,9662.3
XS GIS Cut Line= 4
     1858613.757       438943.33     1859698.318      436642.633
     1860590.117      434706.386     1861045.846      433742.844
#Sta/Elev= 30
       0 1265.34   319.2 1248.15   688.2 1177.19   917.7 1156.77  1067.3 1122.83
  1206.9 1117.46  1386.5 1078.23  1506.2 1075.42  1745.6 1052.78  2034.8  987.88
  2074.7  958.31  2094.7  965.03  2134.6  995.26  2274.2 1029.91  2383.9 1070.92
  2702.9 1132.15  2832.4 1133.81  2902.1 1124.76  3041.6 1050.65  3121.3  989.39
  3220.9   901.4 3267.73  870.12  3270.7   869.7  4326.6  869.85    4476  911.04
  4764.9   970.2  5432.3 1005.39  5591.7  989.63  5671.4  996.44  5741.2 1018.52
#Mann= 3 , 0 , 0
       0      .1       0 3267.73     .04       0  4326.6      .1       0
Bank Sta=3267.73,4326.6
XS Rating Curve= 0 ,0
Exp/Cntr=0.3,0.1

Type RM Length L Ch R = 1 ,10118.3 ,3980.9,3996.7,4012.5
XS GIS Cut Line= 4
     1866796.853      439548.566     1867873.248      438683.278
     1869963.572      437122.466     1873871.986      434242.405
#Sta/Elev= 30
       0  1094.2   129.2 1054.41   476.9 1157.09   735.2 1180.98  1003.5 1172.05
  1680.9 1015.34  1990.8  989.52  2180.7  870.04  2190.7   869.7  4089.7  871.76
  4209.6  941.25  4369.4 1081.19  4419.4 1094.89  5048.7 1076.58  5358.4 1002.41
  5538.2  898.91  5628.1  969.23    5698  995.06  5897.8  945.09  6007.7  950.83
  6197.5 1013.94    6647 1061.58  6896.8  1057.7  6986.7 1031.96  7126.6 1089.34
    7656 1192.06  7735.9 1228.06  7895.8 1220.71  8145.5 1272.92  8844.8 1328.87
#Mann= 3 , 0 , 0
       0      .1       0  2180.7     .04       0  4089.7      .1       0
Bank Sta=2180.7,4089.7
XS Rating Curve= 0 ,0
Exp/Cntr=0.3,0.1

Type RM Length L Ch R = 1 ,6121.6  ,1033.9,1045.4,1057
XS GIS Cut Line= 5
     1868952.964      440666.021     1870006.783      440735.031
     1872064.075      440852.219     1873756.783      441229.823
     1876308.867      441386.073
#Sta/Elev= 30
       0 1061.32     279 1060.96   657.6 1027.08   846.8  989.93  1135.7  950.84
  1314.9  897.36  1354.7  871.64  1374.6   869.7  2808.1  874.71  3007.2  879.35
  3066.9     900    3316  939.52  3804.4   942.7  4641.7  996.62    4891  995.43
  4980.9  972.58  5050.8  928.45  5080.7  945.16  5130.7  953.98  5260.5  1013.8
  5410.3 1053.23    5700 1085.73  5899.7 1129.97  6099.5 1159.99    6479 1205.36
  6638.8 1204.63  6918.5 1190.08  6948.4 1182.86  7108.2 1192.97  7407.9 1230.56
#Mann= 3 , 0 , 0
       0      .1       0  1354.7     .04       0  2808.1      .1       0
Bank Sta=1354.7,2808.1
XS Rating Curve= 0 ,0
Exp/Cntr=0.3,0.1

Type RM Length L Ch R = 1 ,5076.1  ,3578.9,3581.2,3583.5
XS GIS Cut Line= 5
      1868573.19      440676.872     1869863.554      441242.844
     1871400.013      442141.281     1872248.864      444352.487
     1873576.002      446252.591
#Sta/Elev= 30
       0 1028.48   239.8  1042.3   669.5 1025.66  1019.3  978.48    1419  955.82
    1629  932.87    1769  870.24    1779   869.7  2778.9  869.73  2818.9  881.62
  2938.9  946.19  2998.9  963.95  3038.9  989.96  3128.9  1028.5  3348.8 1083.46
  3498.7 1100.92  3978.4 1117.31  4148.3 1109.19  4478.1 1068.44    4638 1039.06
  4797.9 1001.76  4877.8  969.83  4957.8 1013.68  5157.7 1050.73  5697.3 1087.39
  6516.5 1071.46  6786.2 1051.52  7105.9  998.49  7395.6 1080.64  7875.1 1173.23
#Mann= 3 , 0 , 0
       0      .1       0    1769     .04       0  2778.9      .1       0
Bank Sta=1769,2778.9
XS Rating Curve= 0 ,0
Exp/Cntr=0.3,0.1

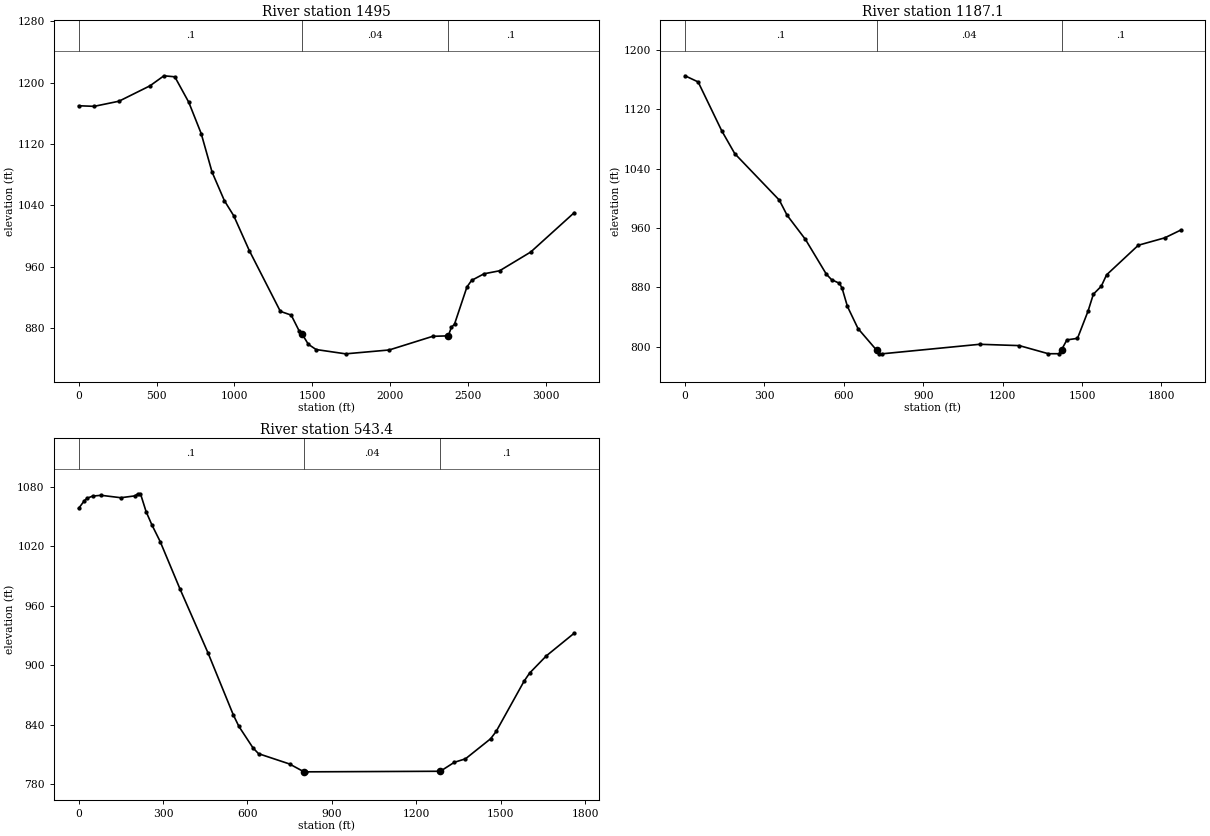
Type RM Length L Ch R = 1 ,1495    ,306.4,307.9,309.4
XS GIS Cut Line= 3
     1866682.999      443108.295     1867672.582      443863.504
     1869236.044      445006.297
#Sta/Elev= 30
       0 1169.79    99.6 1169.02   258.9 1175.71   458.1  1195.8   547.7 1208.88
   617.4 1207.54   707.1 1174.31   786.7 1133.57   856.4 1083.32   936.1 1045.81
   995.9 1026.23  1095.5  980.94  1294.8  901.66  1364.6  896.74  1414.5  876.57
  1434.5  872.06  1474.4   858.7  1524.3  851.84    1714  846.23  1993.5  851.27
    2273  869.07  2372.8   869.7  2392.8  880.84  2412.8  884.92  2492.6  933.41
  2522.6  942.02  2602.4  950.63  2702.3  954.55  2901.9  978.99  3181.4 1030.36
#Mann= 3 , 0 , 0
       0      .1       0  1434.5     .04       0  2372.8      .1       0
Bank Sta=1434.5,2372.8
XS Rating Curve= 1 ,0
   97986     877
Exp/Cntr=0.3,0.1

Type RM Length L Ch R = 1 ,1187.1  ,655.2,643.7,632.2
XS GIS Cut Line= 3
     1867132.652      443832.254     1867611.818      444165.587
     1868600.533      444992.844
#Sta/Elev= 30
       0 1164.94    49.5 1156.66   138.5 1091.02     188 1060.12   356.2  997.61
   385.8  977.17   455.1  944.64   534.2  897.82     554  890.45   583.7  885.61
   593.7  878.84   613.7  854.48   653.7  824.73   723.6  795.76   733.6  790.78
   743.6   790.7  1113.4  803.55  1263.3  801.77  1373.2  790.83  1413.2  790.87
  1423.2  796.41  1443.1  809.48  1483.1  811.54  1523.1   848.3  1543.1  870.98
    1573  881.69    1593     897    1713  936.87  1812.9  946.82  1872.9  957.19
#Mann= 3 , 0 , 0
       0      .1       0   723.6     .04       0  1423.2      .1       0
Bank Sta=723.6,1423.2
XS Rating Curve= 0 ,0
Exp/Cntr=0.3,0.1

Type RM Length L Ch R = 1 ,543.4   ,535.9,543.4,550.9
XS GIS Cut Line= 3
     1866663.007      444760.584     1867510.229      444955.029
     1868385.229       445128.64
#Sta/Elev= 30
       0 1058.43      20 1066.05      30 1068.68      50 1070.86    79.9 1071.64
   149.9  1069.2   199.8 1071.05   209.8 1072.98   219.8 1073.18   239.8 1055.15
   259.8 1042.12   289.8 1024.95   359.7  977.44   459.6  912.68   549.5  850.13
   569.5   838.4   619.5  816.74   639.4  810.82   749.4  800.44   799.3  792.76
   809.3   792.5  1285.5  793.08  1335.1  802.12  1374.8  805.64    1464  825.86
  1483.8  833.27  1582.9  883.93  1602.7  892.19  1662.2  909.59  1761.3  932.48
#Mann= 3 , 0 , 0
       0      .1       0   799.3     .04       0  1285.5      .1       0
Bank Sta=799.3,1285.5
XS Rating Curve= 0 ,0
Exp/Cntr=0.3,0.1

Chan Stop Cuts=-1
Use User Specified Reach Order=0
Composite Channel Slope=5